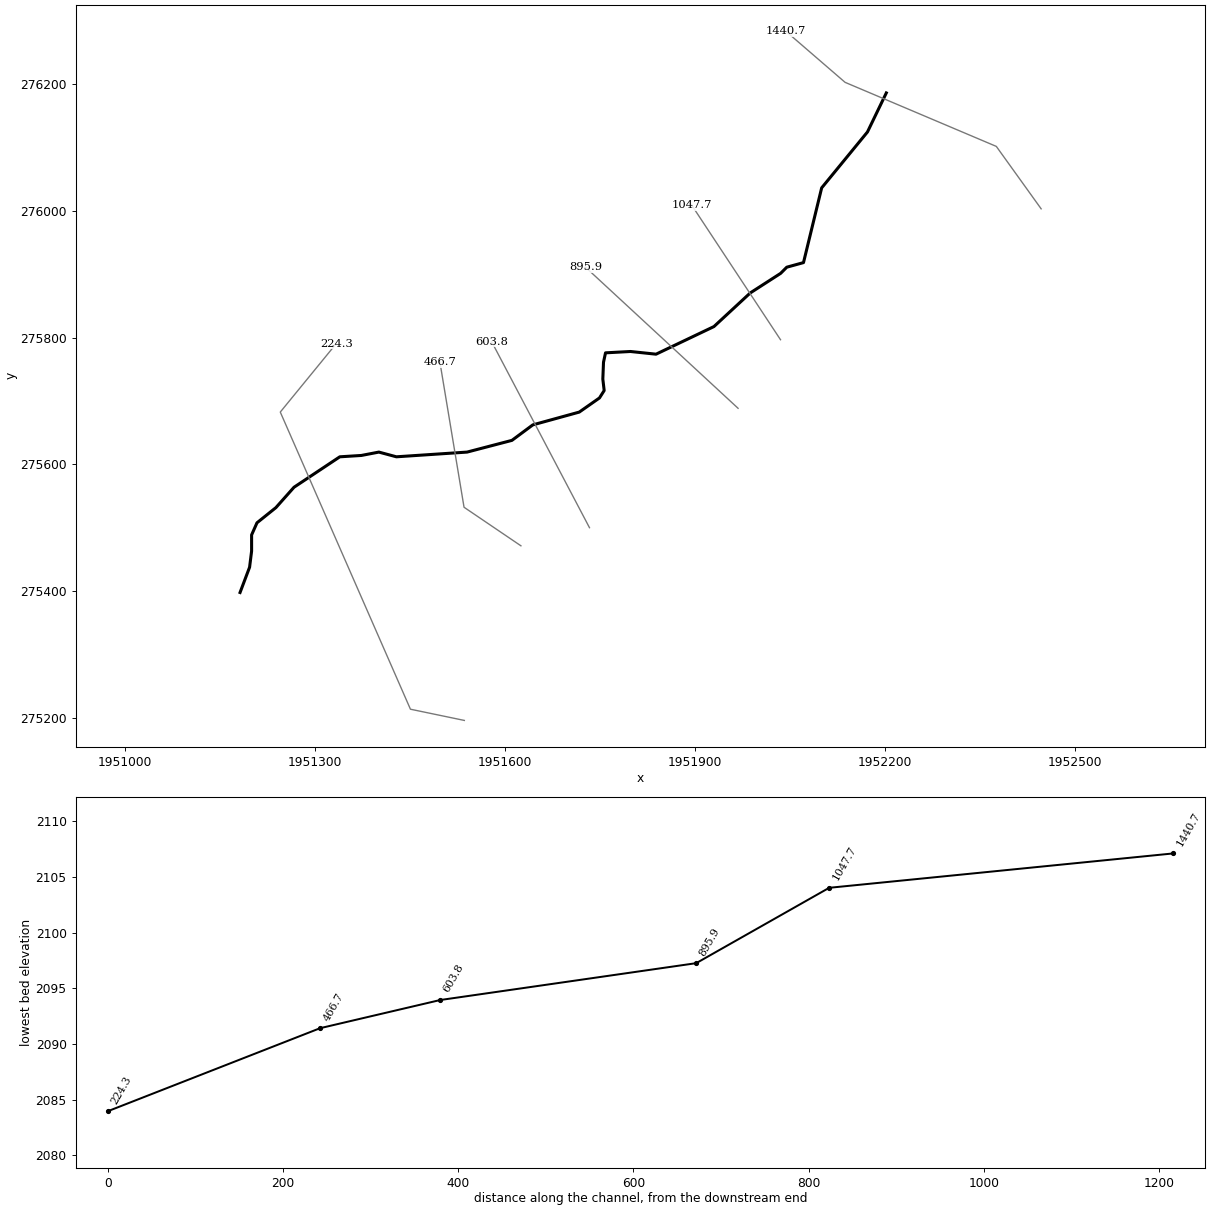
--- BEARRN.prj (project) ---

Proj Title=BEARRN
Current Plan=p01
Geom File=g01
Flow File=f01
Plan File=p01
DSS Export Rating Curves=0
DSS Export Rating Curve Sorted=0
DSS Export Volume Flow Curves=0
DXF OffsetX=0
DXF OffsetY=0
DXF ScaleX=0
DXF ScaleY=0

--- BEARRN.p01 (plan) ---

Plan Title=Floodplain
Program Version=4.00
Geom File=g01
Flow File=f01
K Sum by GR=0
Std Step Tol=0.01
Critical Tol=0.01
Num of Std Step Trials=20
Max Error Tol=0.3
Flow Tol Ratio=0.001
Split Flow NTrial=30
Split Flow Tol=0.02
Split Flow Ratio=0.02
Log Output Level=0
Friction Slope Method=1
Unsteady Friction Slope Method=2
Unsteady Bridges Friction Slope Method=1
Global Log Level=0
CheckData=False
Run HTab=0
Run UNet=0
Run PostProcess=0
UNET Theta=0
UNET Theta Warmup=0
UNET ZTol=0
UNET ZSATol=0
UNET MxIter=0
UNET MaxInSteps=0
UNET DtIC=0
UNET DtMin=0
UNET MaxCRTS=0
UNET WFStab=0
UNET SFStab=0
UNET WFX=0
UNET SFX=0
UNET DSS MLevel=0
UNET DZMax Abort=0
UNET Convert EG Bridges=0
UNET Use Existing IB Tables=0
UNET Froude Limit=0
UNET Froude Power=0
Write IC File=0
Echo Input=False
Echo Output=False
Write Detailed=0

--- BEARRN.f01 (steady flow) ---

Flow Title=NFF Regression Equation
Program Version=4.10
Number of Profiles= 1
Profile Names=P100yr
River Rch & RM=BEARRN,Main            ,1440.7
517.5811
River Rch & RM=BEARRN,Main            ,224.3
529.6891
Boundary for River Rch & Prof#=BEARRN,Main            , 1
Up Type= 0
Dn Type= 3
Dn Slope=0.01991
DSS Import GetInterval= 0
DSS Import GetPeak= 0
DSS Import FillOption= 0

--- BEARRN.g01 (geometry) ---

Geom Title=USGS 10m DEM
Program Version=4.10

River Reach=BEARRN          ,Main
Reach XY= 30
     1952202.806      276186.616     1952173.034      276124.947
     1952100.733      276036.696     1952072.025      275918.674
      1952045.65      275911.438     1952035.874      275901.662
     1951988.027      275870.827     1951930.611      275817.665
      1951839.17      275774.071     1951798.767      275778.324
     1951759.426      275776.197     1951756.236      275761.312
     1951755.173       275734.73     1951757.299      275716.655
     1951749.857      275704.959     1951717.959       275682.63
     1951644.594      275662.428     1951611.632      275637.973
     1951540.819      275619.473     1951429.177       275612.03
     1951401.532      275619.473     1951373.887      275614.156
     1951339.863       275612.03     1951267.561       275563.97
     1951238.944      275531.797     1951209.082       275507.83
     1951200.575      275488.691     1951200.575      275463.173
     1951197.386      275437.655     1951182.337      275397.744

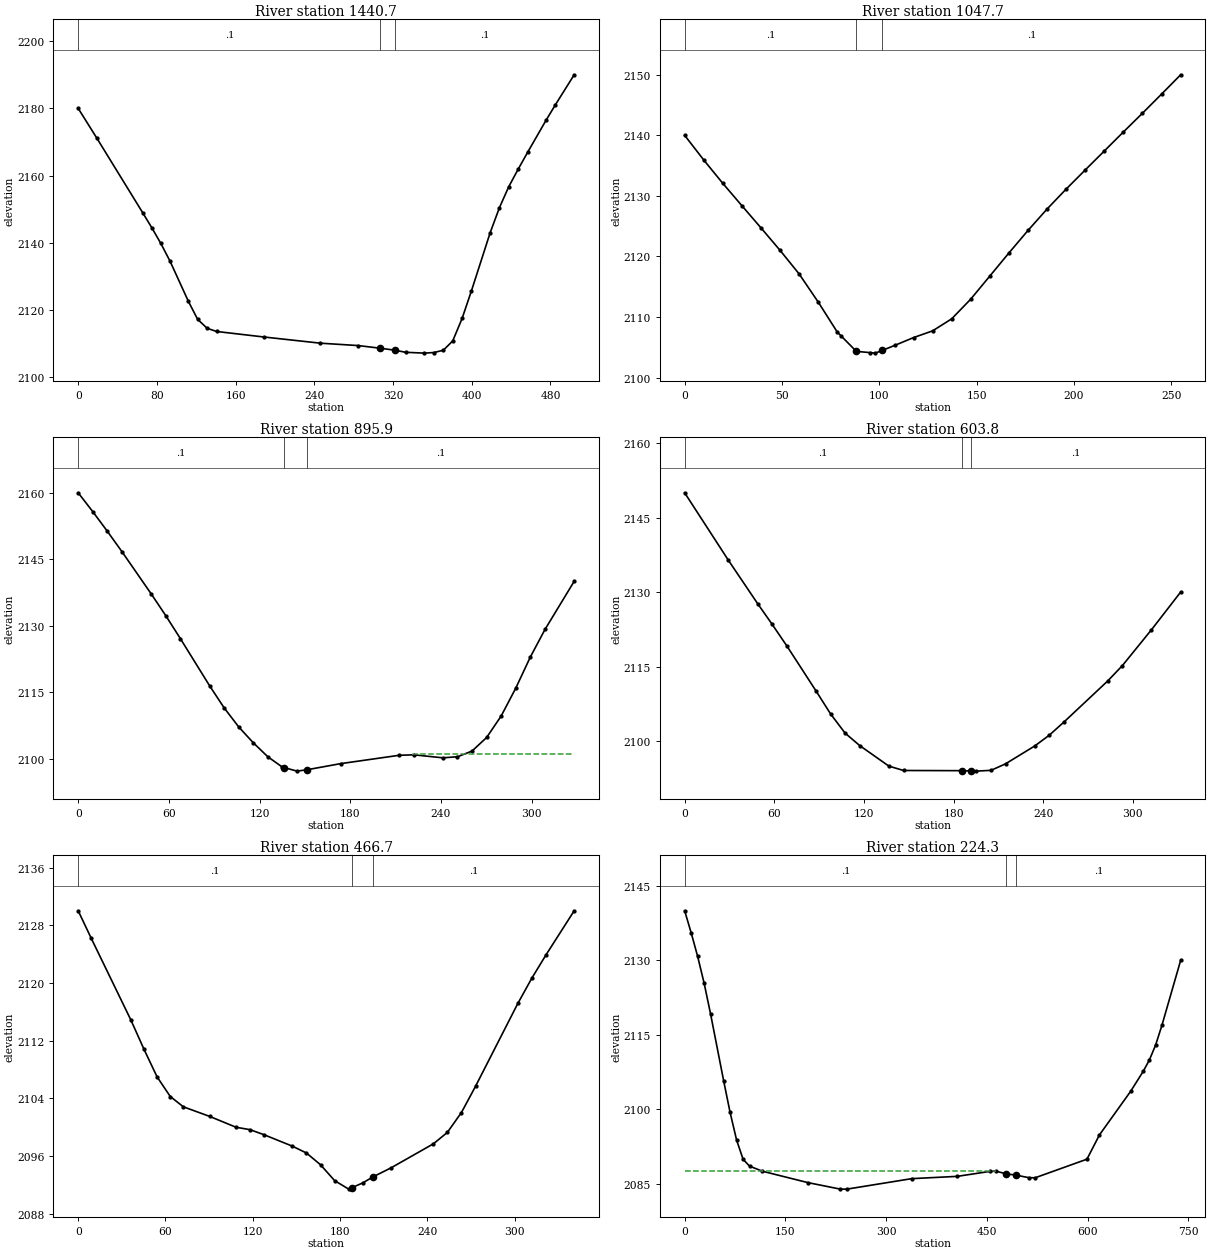
Type RM Length L Ch R = 1 ,1440.7  ,407.6,393,377.6
XS GIS Cut Line= 4
     1952447.302       276003.58     1952376.517      276102.156
     1952137.695      276203.321     1952044.274       276283.94
#Sta/Elev= 30
       0    2180    18.7 2171.25    65.4    2149    74.7 2144.51      84 2139.78
    93.4 2134.46     112 2122.53   121.4 2117.18     131 2114.53   140.6 2113.57
   188.6 2111.93   246.2 2110.08   284.7 2109.37   307.2 2108.57   322.2 2107.98
   332.7 2107.37   351.9 2107.12   361.5  2107.3   371.1 2107.97   380.7 2110.77
   390.2 2117.44   399.7 2125.67   418.7 2142.95   428.2 2150.48   437.7 2156.73
   447.2  2161.9   456.7 2166.87   475.6  2176.5   485.1 2181.11   504.1    2190
#Mann= 3 , 0 , 0
       0      .1       0   307.2    .045       0   322.2      .1       0
Bank Sta=307.2,322.2
XS Rating Curve= 0 ,0
Exp/Cntr=0.3,0.1

Type RM Length L Ch R = 1 ,1047.7  ,145.6,151.8,157.3
XS GIS Cut Line= 2
     1952035.754       275796.89     1951895.393      276009.597
#Sta/Elev= 30
       0    2140     9.8 2135.93    19.6 2132.07    29.4 2128.38    39.2 2124.72
      49 2121.01    58.8 2117.11    68.6 2112.47    78.4 2107.51    80.4 2106.86
    88.2 2104.32    95.4 2104.11      98 2104.03  101.412104.469   107.8 2105.29
   117.6  2106.6   127.4 2107.71   137.2  2109.7     147 2112.96   156.8 2116.77
   166.6 2120.58   176.4  2124.3   186.2 2127.84     196 2131.13   205.8 2134.29
   215.6 2137.42   225.4 2140.56   235.2 2143.66     245 2146.81   254.8    2150
#Mann= 3 , 0 , 0
       0      .1       0    88.2    .045       0  101.41      .1       0
Bank Sta=88.2,101.41
XS Rating Curve= 0 ,0
Exp/Cntr=0.3,0.1

Type RM Length L Ch R = 1 ,895.9   ,294.7,292.2,286.2
XS GIS Cut Line= 2
     1951968.737      275688.623     1951727.804      275911.442
#Sta/Elev= 28
       0    2160     9.6 2155.78    19.3 2151.32      29 2146.71    48.3 2137.22
    57.9 2132.33    67.6 2127.14    86.9 2116.53    96.5 2111.56   106.2 2107.23
   115.8 2103.67   125.5 2100.49   135.1 2098.17   136.4 2098.05   144.8 2097.26
   151.4 2097.57   173.7 2098.95   212.4 2100.83     222 2100.94   241.3 2100.26
     251  2100.5   260.6 2101.78   270.3 2104.85   279.9 2109.69   289.6 2115.99
   299.2 2122.98   308.9  2129.2   328.2 2140.04
#Mann= 3 , 0 , 0
       0      .1       0   136.4    .045       0   151.4      .1       0
#XS Ineff= 2 , 0
                          221.34         2101.09
Permanent Ineff=
       F       F
Bank Sta=136.4,151.4
XS Rating Curve= 0 ,0
Exp/Cntr=0.3,0.1

Type RM Length L Ch R = 1 ,603.8   ,144.4,137.1,129.8
XS GIS Cut Line= 2
      1951734.09      275500.114     1951579.522      275793.979
#Sta/Elev= 23
       0    2150    29.3  2136.4    48.8  2127.7    58.6  2123.5    68.4 2119.16
    87.9 2110.11    97.7 2105.46   107.4  2101.6   117.2 2099.09   136.7 2094.96
   146.5 2094.08   185.6 2094.04     192 2093.98   195.3 2093.95   205.1 2094.11
   214.8 2095.42   234.4 2099.03   244.1 2101.19   253.9 2103.84   283.2 2112.11
     293  2115.2   312.5 2122.43     332    2130
#Mann= 3 , 0 , 0
       0      .1       0   185.6    .045       0     192      .1       0
Bank Sta=185.6,192
XS Rating Curve= 0 ,0
Exp/Cntr=0.3,0.1

Type RM Length L Ch R = 1 ,466.7   ,236.4,242.4,247.9
XS GIS Cut Line= 3
     1951625.824      275471.503      1951536.02      275532.366
     1951497.873      275761.781
#Sta/Elev= 28
       0    2130       9 2126.17    36.2 2114.87    45.2 2110.82    54.2 2106.99
    63.3 2104.26    72.3 2102.83    90.4  2101.5   108.5    2100   118.2 2099.66
   127.9 2098.95   147.2 2097.38   156.9 2096.43   166.6  2094.8   176.3  2092.6
     186 2091.42     188  2091.6   195.7 2092.29     203 2093.15   215.1 2094.37
   244.2  2097.7   253.8 2099.28   263.5 2102.04   273.2 2105.68   302.3 2117.17
     312  2120.7   321.7 2123.91     341    2130
#Mann= 3 , 0 , 0
       0      .1       0     188    .045       0     203      .1       0
Bank Sta=188,203
XS Rating Curve= 0 ,0
Exp/Cntr=0.3,0.1

Type RM Length L Ch R = 1 ,224.3   ,206,224.3,242.5
XS GIS Cut Line= 4
     1951536.498      275195.759     1951451.373      275213.475
     1951245.859      275682.669     1951334.168      275790.663
#Sta/Elev= 30
       0    2140     9.7 2135.56    19.3 2130.83      29 2125.41    38.6 2119.21
      58  2105.8    67.6 2099.43    77.3 2093.86      87 2089.97    96.6 2088.59
   115.9 2087.56   183.6 2085.27   231.9 2083.96   241.6 2083.96   338.2 2086.07
   405.9 2086.53   454.2 2087.52   463.9 2087.57   478.8 2087.04   493.8 2086.77
   512.2 2086.28   521.9 2086.24   599.2 2089.99   617.8 2094.88   664.3 2103.66
   682.9 2107.66   692.2 2109.97   701.5 2112.99   710.8 2116.92   738.7    2130
#Mann= 3 , 0 , 0
       0      .1       0   478.8    .045       0   493.8      .1       0
#XS Ineff= 2 , 0
           463.1  2087.6
Permanent Ineff=
       F       F
Bank Sta=478.8,493.8
XS Rating Curve= 0 ,0
Exp/Cntr=0.3,0.1

Chan Stop Cuts=-1
Use User Specified Reach Order=0
Composite Channel Slope=5